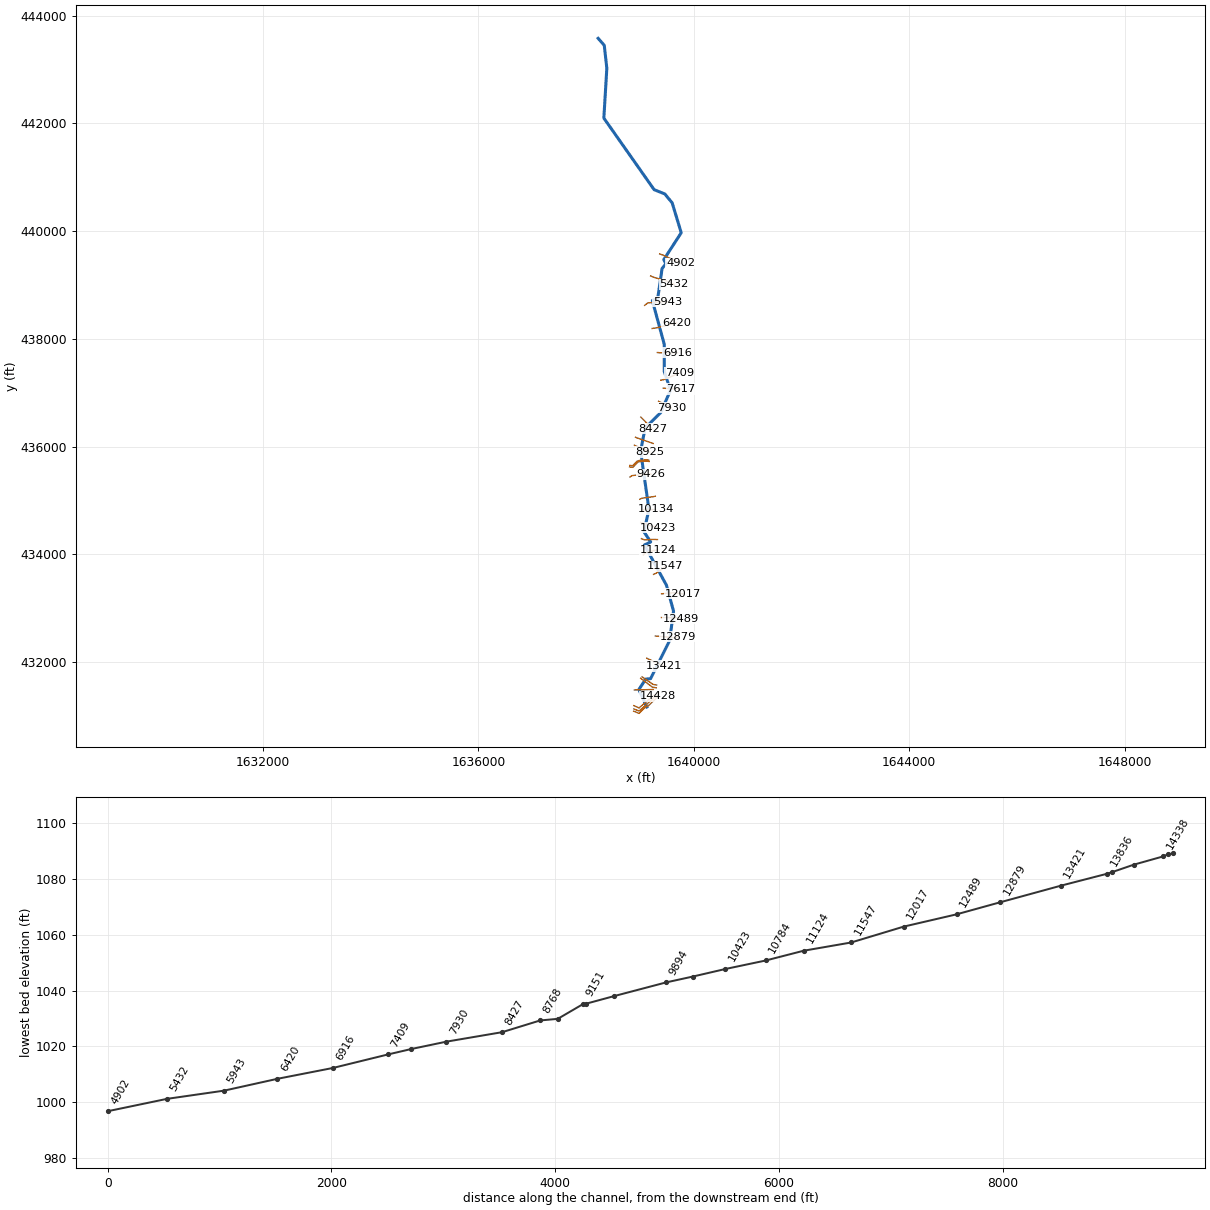
--- MFKLYNCPRN.prj (project) ---

Proj Title=MFKLYNCPRN
Current Plan=p01
Default Exp/Contr=0,0
English Units
Geom File=g01
Flow File=f01
Plan File=p01
BEGIN DESCRIPTION:
---------- MODELED AS PART OF WVEMD CTP PROGRAM, 2023----------
Stream Name: Middle Fork Lynn Camp Run
Flood Zone:  AFH
Wetzel County, WV
HEC-RAS Version: RAS 6.3
Vertical Datum: NAVD88
Projection: NAD 1983 StatePlane West Virginia S FIPS 4702 (US Feet)
Terrain: 1-meter West Virginia FEMA R3 South Central (collected 2018-2020)
Land Use: 2019 NLCD
Hydrologic Method:
WV SIR2010-5033 regression equations
Additional Model Notes:
Share XS with Lynn Camp Run with Normal Depth
END DESCRIPTION:
DSS Export Rating Curves= 0
DSS Export Rating Curve Sorted= 0
DSS Export Volume Flow Curves= 0
DXF OffsetX= 0
DXF OffsetY= 0
DXF ScaleX= 0
DXF ScaleY= 0

--- MFKLYNCPRN.p01 (plan) ---

Plan Title=Floodplain
Program Version=6.30
Geom File=g01
Flow File=f01
Subcritical Flow
K Sum by GR= 0
Std Step Tol= 0.01
Critical Tol= 0.01
Num of Std Step Trials= 20
Max Error Tol= 0.3
Flow Tol Ratio= 0.001
Split Flow NTrial= 30
Split Flow Tol= 0.02
Split Flow Ratio= 0.02
Log Output Level= 0
Friction Slope Method= 1
Unsteady Friction Slope Method= 2
Unsteady Bridges Friction Slope Method= 1
Parabolic Critical Depth
Global Vel Dist= 0 , 0 , 0
Global Log Level= 0
CheckData=False
Encroach Param=-1 ,0,0, 0
Mapping Interval=1HOUR
Computation Time Step Use Courant=        0
Computation Time Step Use Time Series=    0
Computation Time Step Count To Double=0
Computation Time Step Max Doubling=0
Computation Time Step Max Halving=0
Computation Time Step Residence Courant=0
Run HTab= 0
Run UNet= 0
Run Sediment= 0
Run PostProcess= 0
Run WQNet= 0
Run RASMapper=-1
UNET Theta= 0
UNET Theta Warmup= 0
UNET ZTol= 0
UNET ZSATol= 0
UNET MxIter= 0
UNET Max Iter WO Improvement= 0
UNET MaxInSteps= 0
UNET DtIC= 0
UNET DtMin= 0
UNET MaxCRTS= 0
UNET WFStab= 0
UNET SFStab= 0
UNET WFX= 1
UNET SFX= 1
UNET Gravity=32.17405
UNET 1D Methodology=Finite Difference
UNET DSS MLevel= 1
UNET Pardiso=0
UNET DZMax Abort= 0
UNET Use Existing IB Tables= 0
UNET Froude Reduction=False
UNET Froude Limit= 0
UNET Froude Power= 0
UNET D1 Cores= 0
UNET WindReference=Eulerian
UNET WindDragFormulation=Hsu (1988)
UNET D2 Coriolis=0
UNET D2 Cores= 0
UNET D2 Theta= 1
UNET D2 Theta Warmup= 1
UNET D2 Z Tol= 0.01
UNET D2 Volume Tol= 0.01
UNET D2 Max Iterations= 20
UNET D2 Equation= 0
UNET D2 RampUpFraction=0.1
UNET D2 TimeSlices= 1
UNET D2 Turbulence Formulation=Non-Conservative (original)
UNET D2 Eddy Viscosity=0.3
UNET D2 Transverse Eddy Viscosity=0.1
UNET D2 Smagorinsky Mixing=0
UNET D2 BCVolumeCheck=0
UNET D2 Cores=0
UNET D2 SolverType=PARDISO (Direct)
UNET D2 Minimum Iterations= 3
UNET D2 Maximum Iterations= 30
UNET D2 Restart Number= 10
UNET D2 Relaxation Coeff=1.3
UNET D2 SOR Precondition Iterations= 10
UNET D2 ILUT Maximum Fill= 8
UNET D2 ILUT Tolerance=1E-08
UNET D2 Convergence Tolerance=0.00001
UNET D1D2 MaxIter= 0
UNET D1D2 ZTol=0.01
UNET D1D2 QTol=0.1
UNET D1D2 MinQTol=1
Write IC File= 0
Write IC File at Fixed DateTime=0
Write IC File at Sim End=0
Echo Input=False
Echo Parameters=False
Echo Output=False
Write Detailed= 0
HDF Write Warmup=0
HDF Write Time Slices=0
HDF Flush=0
HDF Compression= 1
HDF Chunk Size= 1
HDF Spatial Parts= 1
HDF Use Max Rows=0
HDF Fixed Rows= 1
Calibration Method= 0
Calibration Iterations= 20
Calibration Max Change=0.05
Calibration Tolerance=0.2
Calibration Maximum=1.5
Calibration Minimum=0.5
Calibration Optimization Method= 1
WQ AD Non Conservative
WQ ULTIMATE=-1
WQ Max Comp Step=1HOUR
WQ Output Interval=15MIN
WQ Output Selected Increments= 0
WQ Output face flow=0
WQ Output face velocity=0
WQ Output face area=0
WQ Output face dispersion=0
WQ Output cell volume=0
WQ Output cell surface area=0
WQ Output cell continuity=0
WQ Output cumulative cell continuity=0
WQ Output face conc=0
WQ Output face dconc_dx=0
WQ Output face courant=0
WQ Output face peclet=0
WQ Output face adv mass=0
WQ Output face disp mass=0
WQ Output cell mass=0
WQ Output cell source sink temp=0
WQ Output nsm pathways=0
WQ Output nsm derived pathways=0
WQ Create Restart=0
WQ Fixed Restart=0
WQ System Summary=0
WQ Write To DSS=0
Sorting and Armoring Iterations= 10
XS Update Threshold= 0.02
Bed Roughness Predictor= 0
Hydraulics Update Threshold= 0.02
Energy Slope Method= 1
Volume Change Method= 1
Sediment Retention Method= 0
Sediment TS Multiplier= 1
Warm Up Method= 0
XS Weighting Method= 0
Number of US Weighted Cross Sections= 1
Number of DS Weighted Cross Sections= 1
Upstream XS Weight=0
Main XS Weight=1
Downstream XS Weight=0
Number of DS XS's Weighted with US Boundary= 1
Upstream Boundary Weight= 1
Weight of XSs Associated with US Boundary= 0
Number of US XS's Weighted with DS Boundary= 1
Downstream Boundary Weight= 0.5
Weight of XSs Associated with DS Boundary= 0.5
Percentile Method= 0
Sediment Output Level= 3
Mass or Volume Output= 0
Output Increment Type= 1
Profile and TS Output Increment= 1
Transport Output Increment 1
XS Output Flag= 0
XS Output Increment= 10
Read HDF5 Sediment Hotstart= 0
Sediment Hotstart Type= 0
Write Gradation File= 0
Read Gradation Hotstart= 0
Write HDF5 File= 1
Write Binary Output= 1
Write DSS Sediment File= 0
DSS Sediment Output Type= 1
SV Curve= 0
Specific Gage Flag= 0
Subcell Erosion Methods= 0
Subcell Deposition Methods= 0
Advection Scheme= 1
Matrix Solver= 0
Implicit Weighting Factor= 1
Maximum Outer Loop Convergence Iterations= 5
Convergence Maximum Absolute= 0.001
Convergence RMSE= 0.0001
Grain Fractions Max Abs Error= 0.001
Max Subgrid Regions= 1
Max Subgrid Length Scale= 3.402823E+38
Initial Layer Thickness= 3.402823E+38
Min Layer Thickness= 3.402823E+38
Max Layer Thickness= 3.402823E+38
Number of Layers= 5

--- MFKLYNCPRN.f01 (steady flow) ---

Flow Title=Flow
Program Version=6.31
Number of Profiles= 1
Profile Names=F01pct
River Rch & RM=MFKLYNCPRN,Main            ,14428
     726
River Rch & RM=MFKLYNCPRN,Main            ,10784
     818
River Rch & RM=MFKLYNCPRN,Main            ,8427
    1010
River Rch & RM=MFKLYNCPRN,Main            ,7930
    1180
River Rch & RM=MFKLYNCPRN,Main            ,4368
    1330
River Rch & RM=MFKLYNCPRN,Main            ,0
    2350
Boundary for River Rch & Prof#=MFKLYNCPRN,Main            , 1
Up Type= 0
Dn Type= 3
Dn Slope=0.00705
DSS Import GetInterval= 0
DSS Import GetPeak= 0
DSS Import FillOption= 0

--- MFKLYNCPRN.g01 (geometry) ---

Geom Title=Geometry
Program Version=6.31

River Reach=MFKLYNCPRN      ,Main
Reach XY= 30
1639126.62749691431163.2566172931638980.74095491431486.719481845
     1639106.333      431680.248      1639198.42      431689.715
      1639551.71      432395.865     1639624.003      432944.088
     1639492.327      433424.321     1639083.526       434171.35
     1639199.711      434227.292     1639074.059      434417.922
     1639167.868      434831.456     1639012.524      435915.854
     1639096.866       436344.88     1639386.038      436629.749
     1639567.632      437046.726     1639451.635      437392.593
     1639451.635      437898.215     1639230.582      438711.096
     1639330.329      438752.054     1639411.408      439304.841
     1639480.228      439393.164      1639443.45      439471.457
      1639766.93      439970.191     1639598.642      440525.485
     1639462.674       440690.15     1639263.181      440770.672
     1638329.897      442098.731     1638385.242      443025.841
     1638337.406      443451.5931638223.69624282 443580.80252807

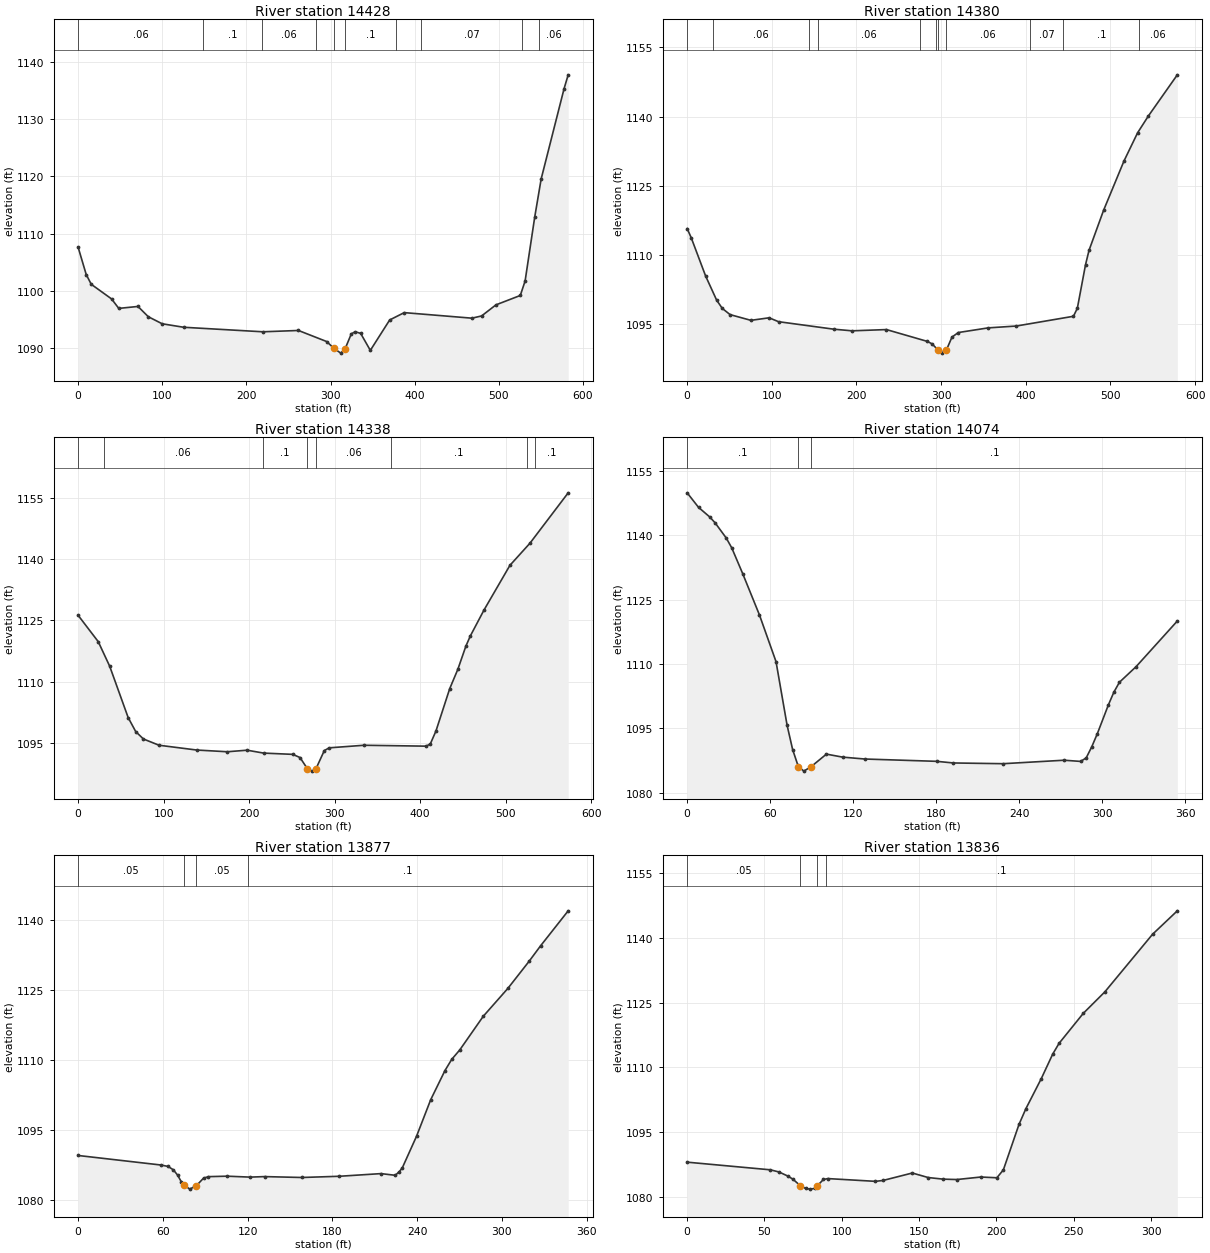
Type RM Length L Ch R = 1 ,14428   ,46.4,48,48.7
XS GIS Cut Line= 6
1638883.10428071 431083.916653371638984.19714612431043.860989716
1639107.47989414431166.0796304631639150.70968037431178.642132443
1639312.03573663431334.9921284991639328.30463053431360.646922734
#Sta/Elev= 30
       0 1107.65     9.7 1102.83    15.7 1101.12    39.8 1098.57    48.4 1096.91
    71.2 1097.25    83.5 1095.45     100 1094.22   125.5 1093.61   219.5 1092.82
   261.9 1093.05   295.5 1091.11   304.2  1089.9   312.2 1089.09   317.21089.802
   324.7 1092.46   329.3 1092.83   335.8 1092.54   347.3 1089.57   370.3 1094.89
   387.6 1096.17     468  1095.2   479.5 1095.59   496.6 1097.53   525.5 1099.17
   531.2  1101.7   542.7 1112.94   550.3 1119.55   577.5 1135.32   582.4 1137.74
#Mann= 10 ,-1,0
       0     .06       0  148.74      .1       0  218.74     .06       0
  282.34      .1       0   304.2    .045       0   317.2      .1       0
  377.35     .06       0  407.35     .07       0  527.35      .1       0
  547.35     .06       0
Bank Sta=304.2,317.2
XS Rating Curve= 0 ,0
Exp/Cntr(USF)=0,0
Exp/Cntr=0.3,0.1

Type RM Length L Ch R = 1 ,14380   ,41.8,41.7,41.7
XS GIS Cut Line= 4
1638887.89040129431126.3858420441638984.70009201431087.138670132
1639252.88910008431326.5464187951639348.39055173431390.650132918
#Sta/Elev= 30
       0 1115.74     4.7  1113.8    21.8 1105.47    34.8 1100.25    41.5 1098.45
    50.7 1097.11    75.3 1095.87    96.8 1096.42   107.9 1095.58   173.4 1093.95
   194.8  1093.6   235.4 1093.87   283.5 1091.32   289.2 1090.79   296.5 1089.43
   300.5 1088.77   306.2 1089.43   312.8 1092.24   320.3 1093.23   355.7 1094.24
   388.9 1094.64   456.3 1096.75   460.9 1098.48   470.6 1107.94   474.7 1111.03
   491.9  1119.7     516 1130.38   532.1 1136.49   544.9 1140.15     579 1149.04
#Mann= 11 ,-1,0
       0     .05       0      30     .06       0  144.46      .1       0
  154.46     .06       0  274.46      .1       0  294.46     .06       0
   296.5    .045       0   306.2     .06       0  404.46     .07       0
  444.46      .1       0  533.96     .06       0
Bank Sta=296.5,306.2
XS Rating Curve= 0 ,0
Exp/Cntr(USF)=0,0
Exp/Cntr=0.3,0.1

Type RM Length L Ch R = 1 ,14338   ,267.5,264.6,261
XS GIS Cut Line= 4
1638886.58216223431187.8730780391638983.39185295431144.701188936
1639231.95727506431359.2523953881639349.69879079431432.513782957
#Sta/Elev= 30
       0 1126.26    23.6 1119.78      37 1113.75    58.6 1101.16    67.4 1097.74
    76.4 1095.92    94.6 1094.39   138.7 1093.21   174.5 1092.79   197.6 1093.17
     217 1092.46     251 1092.15   259.5 1091.37   268.1 1088.63   273.7 1088.04
   278.11088.607   287.9 1093.08   293.6 1093.75   334.2 1094.38     407 1094.16
   411.8  1094.7   418.4 1097.87   434.5 1108.26     444    1113   453.4 1118.68
   458.6 1121.18   474.6 1127.54   504.9 1138.49   528.3 1143.91     573 1156.26
#Mann= 8 ,-1,0
       0     .05       0      30     .06       0     216      .1       0
   268.1    .045       0   278.1     .06       0     366      .1       0
  524.35     .06       0  534.35      .1       0
Bank Sta=268.1,278.1
XS Rating Curve= 0 ,0
Exp/Cntr(USF)=0,0
Exp/Cntr=0.3,0.1

Type RM Length L Ch R = 1 ,14074   ,199.8,197.1,193.7
XS GIS Cut Line= 2
 1638895.8927919431478.2152372371639249.82378821431487.752300011
#Sta/Elev= 30
       0 1149.86     8.2 1146.48    16.2 1144.27    20.2 1142.87    28.2 1139.35
    32.2 1137.05    40.2 1130.98    52.2 1121.44    64.2 1110.55    72.2 1095.72
    76.2 1090.07    80.3 1086.13    84.3 1085.06    89.61086.114   100.6 1089.02
   112.3 1088.32   128.3 1087.88   180.3 1087.34   192.3 1086.96   228.3 1086.79
   272.3  1087.6   284.3 1087.32   288.3 1088.16   292.3 1090.73   296.3 1093.76
   304.3 1100.48   308.3 1103.47   312.3 1105.76   324.3 1109.38   354.1 1120.01
#Mann= 3 ,-1,0
       0      .1       0    80.3    .045       0    89.6      .1       0
Bank Sta=80.3,89.6
XS Rating Curve= 0 ,0
Exp/Cntr(USF)=0,0
Exp/Cntr=0.3,0.1

Type RM Length L Ch R = 1 ,13877   ,40.5,40.8,41.3
XS GIS Cut Line= 3
1639013.40402176 431696.419978631639231.90778143431530.289542795
1639303.42834194  431519.0264624
#Sta/Elev= 30
       0 1089.55    58.7 1087.51    63.7 1087.21    67.5 1086.47    70.4 1085.37
    73.2 1083.86    75.3 1083.17    79.1 1082.35    83.8 1083.11    88.8 1084.69
    92.3 1085.02   105.5 1085.12   121.7 1084.92     132 1085.03   158.4 1084.84
   184.9  1085.1   214.4 1085.67   224.5 1085.31   227.4  1086.1   229.5 1086.91
   239.6 1093.69   249.6 1101.49   259.7 1107.73   264.5 1110.13   270.2 1112.15
   286.8 1119.34   304.2  1125.3   319.2 1131.09   327.3 1134.39   346.9  1141.9
#Mann= 4 ,-1,0
       0     .05       0    75.3    .045       0    83.8     .05       0
     120      .1       0
Bank Sta=75.3,83.8
XS Rating Curve= 0 ,0
Exp/Cntr(USF)=0,0
Exp/Cntr=0.3,0.1

Type RM Length L Ch R = 1 ,13836   ,411.9,414.8,414.4
XS GIS Cut Line= 3
1639039.87226069431722.8882175591639243.73401585431582.099712615
1639311.87565224 431569.71032418
#Sta/Elev= 30
       0 1088.06    53.8 1086.29    59.4 1085.79    65.1 1084.84    68.4 1084.12
    73.2 1082.61    76.6 1081.97    79.5 1081.82    82.4 1081.97    84.21082.601
    88.1 1084.05      91 1084.26   121.8 1083.62   126.7 1083.83   145.6 1085.55
   155.9  1084.5   165.6 1084.13   174.4 1084.04   189.9 1084.62   200.3 1084.45
   204.5 1086.28   214.6 1096.79     219 1100.39     229 1107.38   236.4 1113.06
   240.5 1115.55   256.2 1122.51   270.1 1127.46     301 1140.81     317 1146.23
#Mann= 4 ,-1,0
       0     .05       0    73.2    .045       0    84.2     .05       0
      90      .1       0
Bank Sta=73.2,84.2
XS Rating Curve= 0 ,0
Exp/Cntr(USF)=0,0
Exp/Cntr=0.3,0.1

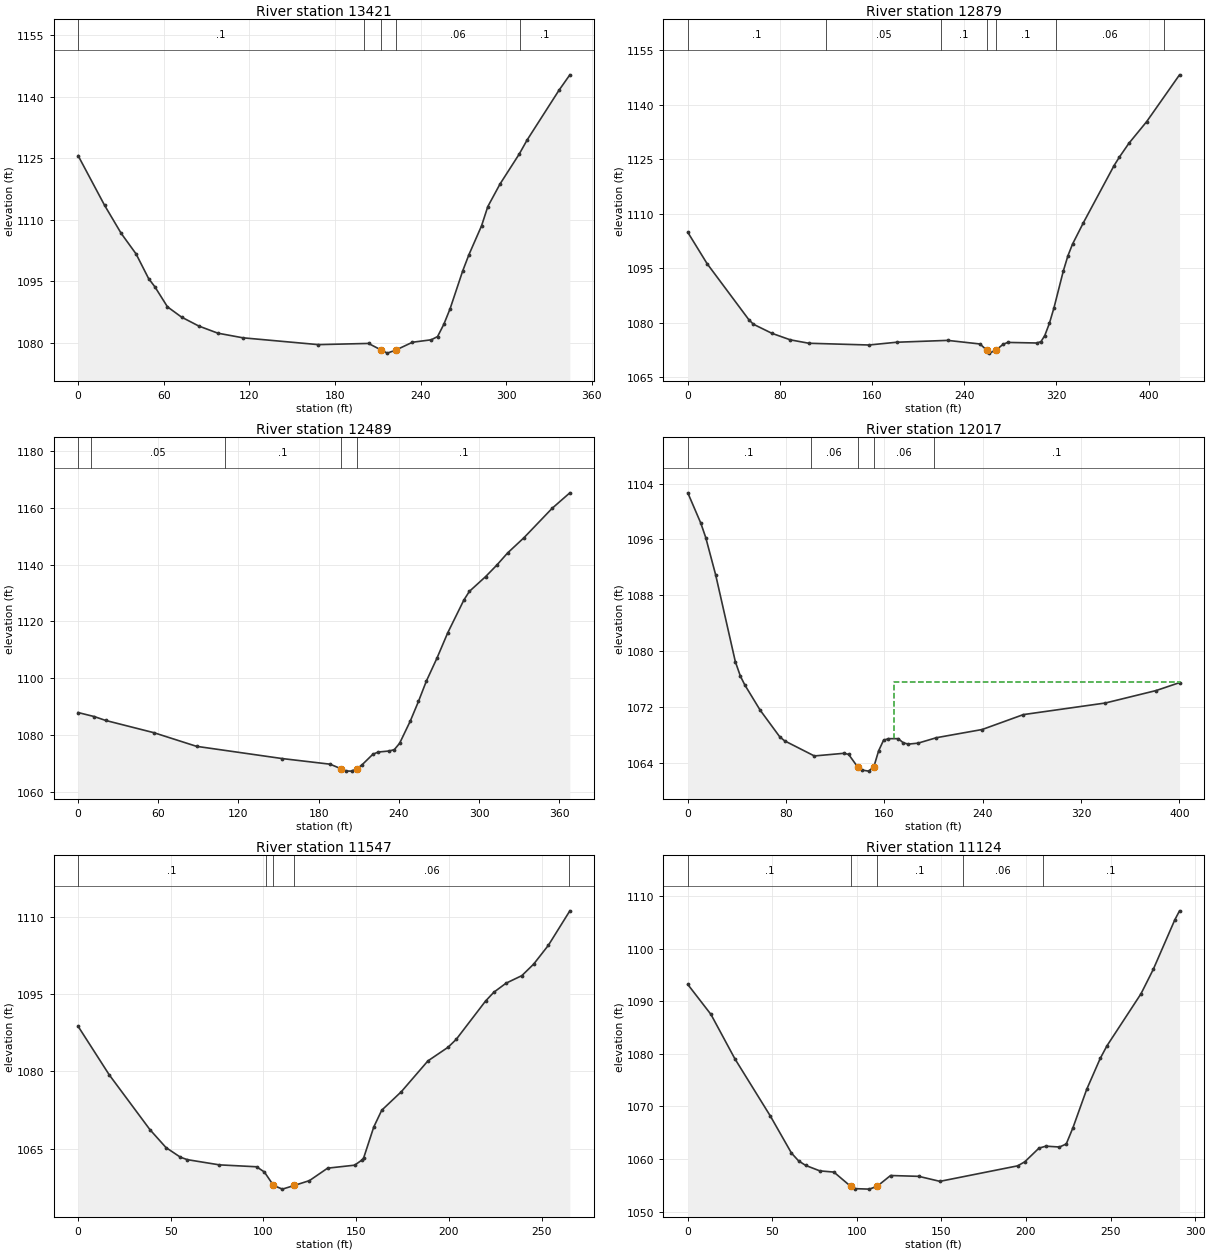
Type RM Length L Ch R = 1 ,13421   ,540.8,542.6,543.6
XS GIS Cut Line= 2
1639127.17081998 432067.690514591639440.36325184431924.045865392
#Sta/Elev= 30
       0 1125.63    18.6  1113.5    30.2 1106.69    40.6  1101.7    49.4 1095.69
    53.8 1093.68    62.6 1088.81    72.5  1086.3    84.5 1084.14    97.9 1082.39
   115.5 1081.26   168.3  1079.6   203.5 1079.89   212.3  1078.3   216.7 1077.53
   222.71078.284   234.3 1080.18   247.5 1080.78   251.9 1081.57   256.3 1084.57
   260.7 1088.37   269.5 1097.55   273.9 1101.54   282.7 1108.52   287.1 1113.23
   295.7 1118.75   309.1 1126.01   314.6 1129.42   336.9 1141.52   344.6 1145.32
#Mann= 5 ,-1,0
       0      .1       0     200     .06       0   212.3    .045       0
   222.7     .06       0     310      .1       0
Bank Sta=212.3,222.7
XS Rating Curve= 0 ,0
Exp/Cntr(USF)=0,0
Exp/Cntr=0.3,0.1

Type RM Length L Ch R = 1 ,12879   ,387.7,389.4,388.9
XS GIS Cut Line= 3
1639287.43538971432480.5357542781639639.35300609432449.063447122
 1639710.8809769432466.230160116
#Sta/Elev= 30
       0 1104.87    16.7 1096.26    52.9 1080.84    56.9 1079.56      73 1077.05
      89 1075.25   105.1 1074.31   157.3 1073.83   181.3 1074.59   225.6  1075.1
   253.7 1074.11   259.71072.357   261.7 1071.59   267.41072.375   273.8 1074.04
   277.8 1074.54   302.9 1074.38   306.6 1074.75   309.9 1076.42   313.9 1079.77
   317.9 1084.07     326  1094.2     330  1098.4     334 1101.62   343.4 1107.49
   370.1 1123.27   374.7 1125.59   382.9 1129.37   398.4 1135.37   426.9 1148.25
#Mann= 7 ,-1,0
       0      .1       0     120     .05       0     220      .1       0
   259.7    .045       0   267.4      .1       0     320     .06       0
  413.32      .1       0
Bank Sta=259.7,267.4
XS Rating Curve= 0 ,0
Exp/Cntr(USF)=0,0
Exp/Cntr=0.3,0.1

Type RM Length L Ch R = 1 ,12489   ,470.5,472,471.7
XS GIS Cut Line= 3
1639399.52180232432824.1550768851639684.67997928 432822.24766433
1639765.74501287432805.080951335
#Sta/Elev= 30
       0  1087.9    12.1 1086.48    20.6 1085.12    56.6 1080.82    88.6 1076.01
   152.6 1071.71   188.6 1069.72   196.6 1068.14   200.6 1067.32   204.6 1067.28
   208.6  1068.1   212.6 1069.56   220.6 1073.23   224.6    1074   232.6 1074.36
   236.6 1074.83   240.6 1077.09   248.6 1084.93   254.7 1091.81   260.6 1098.96
   268.6 1107.11   276.6 1115.97   288.7 1127.52   292.8 1130.55     305 1135.77
   313.2 1139.73   321.4 1144.07   333.7 1149.46   354.8 1159.82     368 1165.24
#Mann= 5 ,-1,0
       0      .1       0      10     .05       0     110      .1       0
   196.6    .045       0   208.6      .1       0
Bank Sta=196.6,208.6
XS Rating Curve= 0 ,0
Exp/Cntr(USF)=0,0
Exp/Cntr=0.3,0.1

Type RM Length L Ch R = 1 ,12017   ,465.9,469.7,471.8
XS GIS Cut Line= 3
1639401.54652228433264.5177078131639638.44716161433286.834434705
 1639798.9559281433262.801036513
#Sta/Elev= 30
       0 1102.67    10.6 1098.33    14.6 1096.28    22.7 1090.93    38.7 1078.53
    42.8 1076.47    46.4 1075.21    58.8 1071.63    74.9 1067.78    78.9 1067.21
     103 1065.06   127.1 1065.44   130.9 1065.28   138.2  1063.5   141.9 1063.04
   147.2 1062.89   151.41063.498   155.3 1065.79   159.3  1067.3   163.3 1067.53
   171.3 1067.53   175.3 1066.95   179.4 1066.75   187.4 1066.89   202.4 1067.67
   239.6 1068.84   273.1 1070.97   339.9 1072.63   381.2 1074.41   400.2 1075.54
#Mann= 5 ,-1,0
       0      .1       0     100     .06       0   138.2    .045       0
   151.4     .06       0     200      .1       0
#XS Ineff= 2 , 0
                          167.51         1075.68
Permanent Ineff=
       F       F
Bank Sta=138.2,151.4
XS Rating Curve= 0 ,0
Exp/Cntr(USF)=0,0
Exp/Cntr=0.3,0.1

Type RM Length L Ch R = 1 ,11547   ,425.2,423.6,420.3
XS GIS Cut Line= 4
1639252.68136445433625.8072133261639299.88982518433646.407268919
1639401.17343185433716.7907921961639472.41529078433772.582609428
#Sta/Elev= 30
       0 1088.74    16.8 1079.34    38.7 1068.75    47.4 1065.26    55.2 1063.39
    58.9 1062.92    76.2 1061.91    96.3 1061.54   100.5 1060.52   105.4 1057.93
   110.2 1057.21   116.71057.929   124.8 1058.86   134.6 1061.27   149.2 1061.85
   153.4 1062.92   154.1 1063.31   159.5 1069.24   163.8 1072.49   174.4 1076.09
   188.7 1082.04   199.6 1084.69     204 1086.22   219.8 1093.63   224.3 1095.35
   230.9  1097.1   239.4 1098.56   245.8  1100.8   253.7 1104.43   265.3 1111.11
#Mann= 5 ,-1,0
       0      .1       0  101.51     .06       0   105.4    .045       0
   116.7     .06       0  264.85      .1       0
Bank Sta=105.4,116.7
XS Rating Curve= 0 ,0
Exp/Cntr(USF)=0,0
Exp/Cntr=0.3,0.1

Type RM Length L Ch R = 1 ,11124   ,340,339.4,336.2
XS GIS Cut Line= 4
1639061.75175089433987.5683249641639090.36293921434019.358534212
 1639250.3736591434068.1035217271639330.90885586434074.461563577
#Sta/Elev= 30
       0 1093.19    13.7 1087.49    27.8 1079.08    48.8 1068.18    61.3 1061.13
    65.5 1059.65    69.7 1058.78    78.1 1057.74    86.4 1057.51    96.4 1054.78
      99 1054.36   107.3 1054.27   111.91054.788   119.9 1056.86   136.6  1056.7
   149.1 1055.75   195.1  1058.7   199.3 1059.47   207.7 1062.07   211.8 1062.44
   219.8 1062.28   223.8 1062.85   227.8 1065.97   235.9 1073.24   243.9 1079.12
   247.9 1081.53     268 1091.41   275.3 1096.08     288 1105.47   290.8 1107.19
#Mann= 5 ,-1,0
       0      .1       0    96.4    .045       0   111.9      .1       0
  162.77     .06       0  210.04      .1       0
Bank Sta=96.4,111.9
XS Rating Curve= 0 ,0
Exp/Cntr(USF)=0,0
Exp/Cntr=0.3,0.1

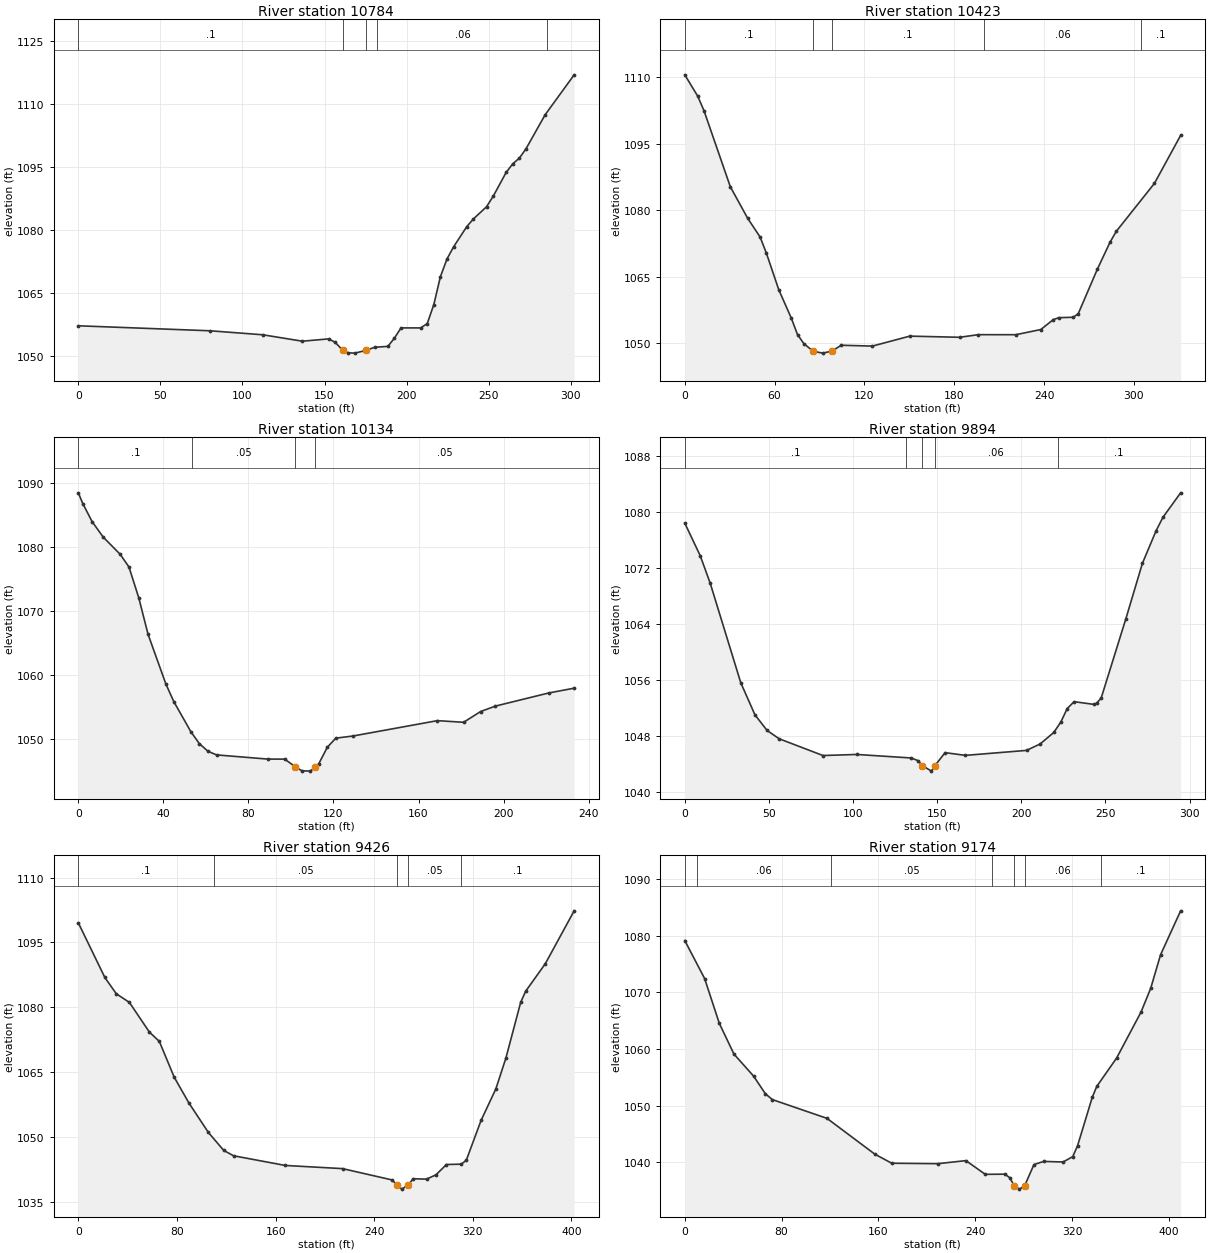
Type RM Length L Ch R = 1 ,10784   ,363.5,361.6,360.1
XS GIS Cut Line= 4
1639028.79139447434289.0374812121639086.01377112434264.664987455
1639249.20351193434275.2617238711639325.50001413434272.082702946
#Sta/Elev= 30
       0 1057.28    80.3 1056.09   112.4 1055.14   136.5 1053.61   152.5 1054.16
   156.5 1053.35   161.11051.422   164.5 1050.84   168.5 1050.77   175.11051.408
   180.5 1052.16   188.6 1052.38   192.6 1054.34   196.6 1056.78   208.6 1056.77
   212.6 1057.81   216.6 1062.34   220.6 1068.96   224.6 1073.17   228.6 1076.06
   236.7 1080.91   240.7 1082.72   248.7 1085.62   252.7 1088.07   260.7 1093.83
   264.7 1095.85   268.7  1097.2   272.7 1099.39   284.4 1107.52   302.1 1117.04
#Mann= 5 ,-1,0
       0      .1       0   161.1    .045       0   175.1      .1       0
   182.2     .06       0  285.73      .1       0
Bank Sta=161.1,175.1
XS Rating Curve= 0 ,0
Exp/Cntr(USF)=0,0
Exp/Cntr=0.3,0.1

Type RM Length L Ch R = 1 ,10423   ,287.3,289.3,289.8
XS GIS Cut Line= 3
1639015.83982774434585.9815838991639270.16150173434511.804428985
1639332.56450507434489.433540995
#Sta/Elev= 30
       0 1110.58     8.6 1105.78    12.8  1102.5    30.4 1085.31      42 1078.17
    50.3 1073.95    54.5  1070.3    62.8 1062.01    71.1 1055.66    75.3  1051.9
    79.5 1049.88    85.61048.175      92 1047.72    98.2 1048.16   104.5  1049.5
   125.3 1049.31   150.3 1051.56   183.6  1051.3   196.1 1051.89   221.1 1051.88
   237.8 1053.05   246.1 1055.28   249.8 1055.73   259.5 1055.82   262.8 1056.61
   275.5 1066.62     284 1072.74   288.2 1075.22   313.7 1086.06   331.2  1096.9
#Mann= 5 ,-1,0
       0      .1       0    85.6    .045       0    98.2      .1       0
     200     .06       0  304.92      .1       0
Bank Sta=85.6,98.2
XS Rating Curve= 0 ,0
Exp/Cntr(USF)=0,0
Exp/Cntr=0.3,0.1

Type RM Length L Ch R = 1 ,10134   ,236.8,239.5,239.5
XS GIS Cut Line= 4
1639062.18099729434823.0041597941639092.91153289434836.779917135
1639206.29661255434828.3025280021639292.13017752434830.421875285
#Sta/Elev= 30
       0 1088.41     2.1 1086.73     6.5 1083.91    11.7 1081.51    19.7 1078.82
    23.8 1076.86    28.4 1072.07    32.8 1066.35    41.2 1058.59    44.9 1055.87
    52.9 1051.19    56.9 1049.32      61 1048.12      65 1047.56      89 1046.91
    97.1  1046.9   101.9 1045.73   105.1 1045.09   109.1 1045.03   111.5 1045.71
   113.1 1046.19   117.1 1048.75   121.1 1050.17   129.1  1050.5   168.9  1052.9
   181.2 1052.64   189.2 1054.32   196.2 1055.17   221.2 1057.21   233.2 1057.96
#Mann= 4 ,-1,0
       0      .1       0   53.68     .05       0   101.9    .045       0
   111.5     .05       0
Bank Sta=101.9,111.5
XS Rating Curve= 0 ,0
Exp/Cntr(USF)=0,0
Exp/Cntr=0.3,0.1

Type RM Length L Ch R = 1 ,9894    ,465.1,467.7,466.2
XS GIS Cut Line= 4
1638999.18056477435021.0235852781639036.04803965435040.427542606
1639245.39610462435068.2376176571639286.33871511435076.735140589
#Sta/Elev= 30
       0 1078.35     9.2 1073.68    15.1 1069.77    33.3 1055.53    41.7 1050.97
    48.9 1048.74    56.1 1047.55    82.1 1045.16   102.3 1045.31   134.5 1044.81
   138.6 1044.43   141.21043.722   146.6 1042.93   148.6 1043.69   154.7 1045.57
   166.8 1045.18   203.1 1045.89   211.2 1046.81   219.3 1048.45   223.5 1049.94
   227.3 1051.87   231.4 1052.85   243.5 1052.45   244.9 1052.66   247.5 1053.38
   262.2 1064.73     272 1072.62   280.1 1077.25   284.2 1079.19   294.7 1082.68
#Mann= 5 ,-1,0
       0      .1       0  131.66     .06       0   141.2    .045       0
   148.6     .06       0  221.66      .1       0
Bank Sta=141.2,148.6
XS Rating Curve= 0 ,0
Exp/Cntr(USF)=0,0
Exp/Cntr=0.3,0.1

Type RM Length L Ch R = 1 ,9426    ,251.7,252.2,251.8
XS GIS Cut Line= 4
 1638813.7536284435434.0864571241638856.61123294435460.128523785
1639144.97190838435485.3145037081639207.54457724435487.191683774
#Sta/Elev= 30
       0 1099.54    21.5 1086.92    30.8 1083.15    41.4 1081.16    57.7 1074.27
    65.7 1072.15    77.8 1063.85    89.8 1057.86   105.5  1051.1   117.9 1046.96
   125.9 1045.71   167.9 1043.47   214.3 1042.74   254.4 1040.13   258.51038.966
   262.5    1038   267.81039.034   271.6  1040.4   282.5 1040.31   290.1 1041.31
   298.6 1043.69   310.6 1043.77   314.7 1044.67   326.7 1053.89   338.7 1061.18
   346.8 1068.26   358.8 1081.15   362.8 1083.71   378.8  1090.1   402.2 1102.32
#Mann= 5 ,-1,0
       0      .1       0  110.15     .05       0   258.5    .045       0
   267.8     .05       0  310.15      .1       0
Bank Sta=258.5,267.8
XS Rating Curve= 0 ,0
Exp/Cntr(USF)=0,0
Exp/Cntr=0.3,0.1

Type RM Length L Ch R = 1 ,9174    ,22.9,23,23.1
XS GIS Cut Line= 6
1638807.90310052435621.1034819841638868.32328484435612.511044322
1638957.95236046435707.578910356 1638977.9756145435717.590537374
1639111.25539918435729.4793444591639172.57661467435721.970624195
#Sta/Elev= 30
       0 1079.13    16.4 1072.42    28.5 1064.53    40.6  1059.1    56.8 1055.22
    66.6 1052.09    72.4 1051.06   117.5 1047.75   157.1 1041.42     171 1039.83
   208.9 1039.75   232.3 1040.29   248.3 1037.87   264.4  1037.9   268.4  1037.3
   272.4 1035.81   276.5 1035.26   280.71035.808   288.5 1039.59   296.5 1040.15
   312.6 1040.05   320.6    1041   324.6 1042.96   336.7 1051.47   340.4 1053.39
   356.8 1058.39     377 1066.52     385 1070.72   393.1 1076.61   409.7 1084.38
#Mann= 7 ,-1,0
       0      .1       0      10     .06       0  121.03     .05       0
  254.07     .06       0   272.4    .045       0   280.7     .06       0
  344.07      .1       0
Bank Sta=272.4,280.7
XS Rating Curve= 0 ,0
Exp/Cntr(USF)=0,0
Exp/Cntr=0.3,0.1

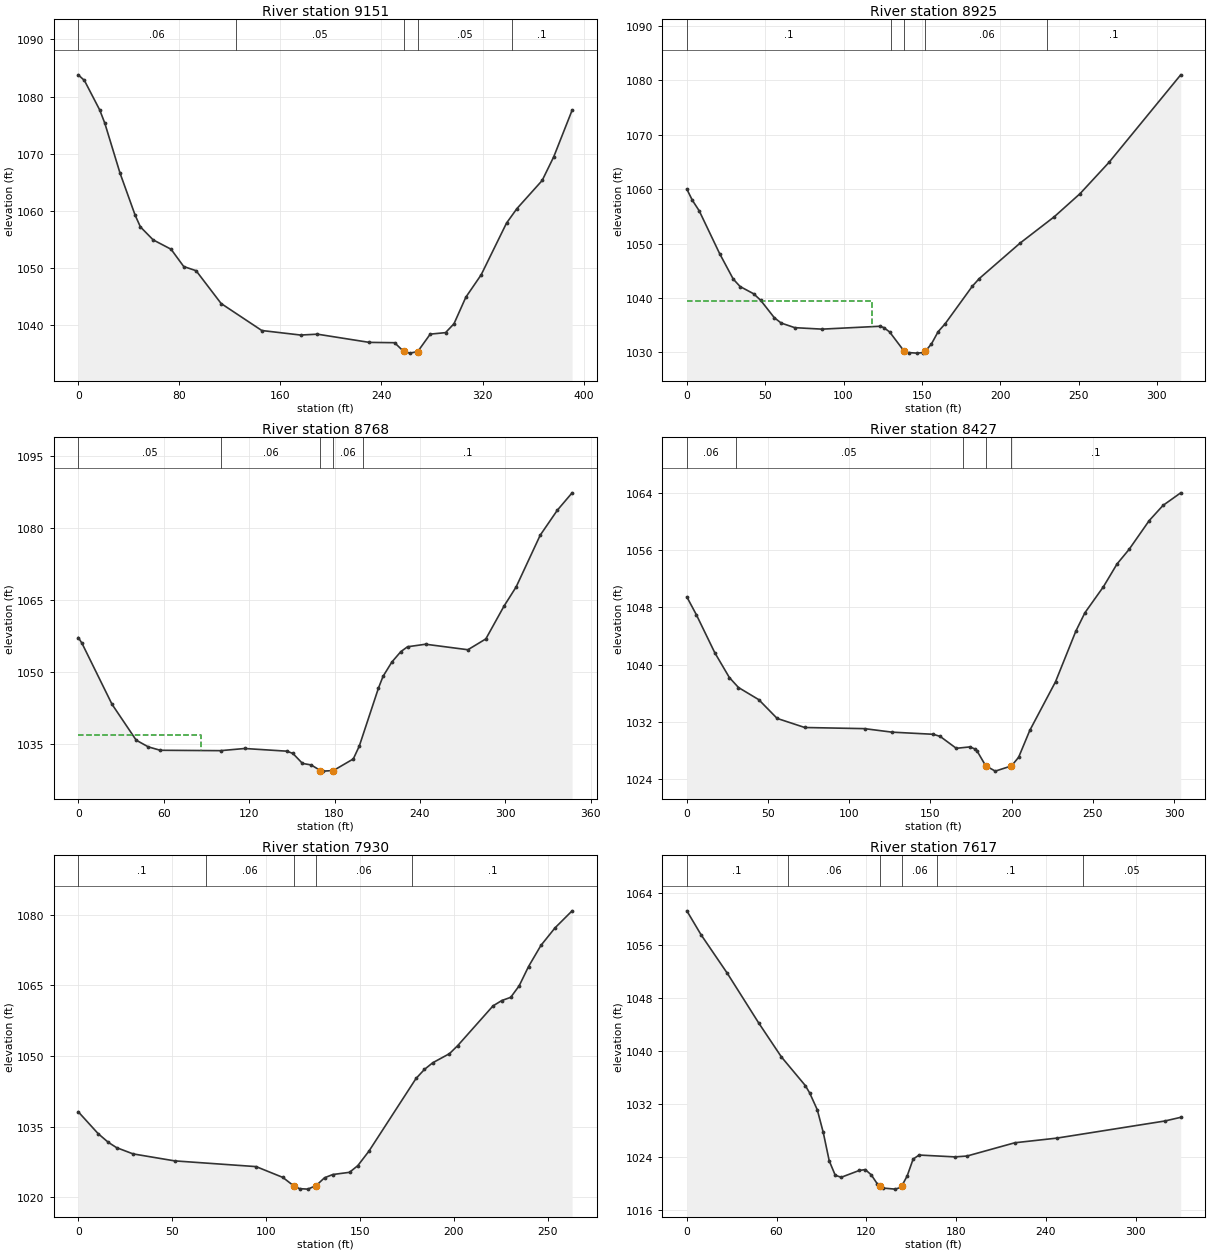
Type RM Length L Ch R = 1 ,9151    ,229.9,226.3,223
XS GIS Cut Line= 6
1638811.23675867435649.0291770711638863.25489867435643.484515411
1638945.73409248435725.8440377061638971.48416197435737.860736802
1639106.24285897435754.169114147 1639163.7513475435748.160764598
#Sta/Elev= 30
       0  1083.8     4.9 1082.81      17 1077.66      21 1075.37    33.1 1066.61
    45.1 1059.24    49.2 1057.23    59.3 1054.96    73.5 1053.32    83.5  1050.3
    93.3 1049.57   113.1 1043.84   145.3 1039.12     176 1038.33   189.3 1038.48
   230.3 1037.05   250.4 1036.99   257.61035.458   262.5 1035.17   268.71035.443
   278.6 1038.49   290.7 1038.75   297.4  1040.3   306.8 1044.95   318.9 1048.85
     339  1057.9   347.2 1060.42   367.2 1065.34   376.4  1069.5   390.9 1077.62
#Mann= 5 ,-1,0
       0     .06       0  124.93     .05       0   257.6    .045       0
   268.7     .05       0  343.13      .1       0
Bank Sta=257.6,268.7
XS Rating Curve= 0 ,0
Exp/Cntr(USF)=0,0
Exp/Cntr=0.3,0.1

Type RM Length L Ch R = 1 ,8925    ,156.5,157.1,157.7
XS GIS Cut Line= 2
 1638896.9086906436023.4741529211639186.16780456435898.157148061
#Sta/Elev= 30
       0 1060.03     3.5 1057.99     7.9 1056.04    20.9 1048.19    29.6  1043.5
      34 1042.12    42.7 1040.78    47.1  1039.6    55.8  1036.4    60.2 1035.41
    68.9 1034.56    86.3 1034.29   123.3 1034.82   125.6 1034.59   129.4 1033.78
   138.6 1030.27   141.5 1029.98   146.7 1029.88   150.7 1029.97   152.31030.257
   156.1 1031.57   160.4 1033.83   164.8 1035.26   182.2 1042.18   186.6 1043.58
   212.7 1050.11   234.5 1054.95     251 1059.21   269.4 1064.94   315.2 1081.04
#Mann= 5 ,-1,0
       0      .1       0     130     .06       0   138.6    .045       0
   152.3     .06       0     230      .1       0
#XS Ineff= 2 , 0
          117.95 1039.41
Permanent Ineff=
       F       F
Bank Sta=138.6,152.3
XS Rating Curve= 0 ,0
Exp/Cntr(USF)=0,0
Exp/Cntr=0.3,0.1

Type RM Length L Ch R = 1 ,8768    ,342.9,340.5,334.7
XS GIS Cut Line= 2
1638917.70255966436170.7682732471639245.17502593436056.443566087
#Sta/Elev= 30
       0 1057.18     2.6    1056    23.7 1043.27    40.7 1035.77    49.2 1034.37
    57.6 1033.66     100 1033.58   116.9 1034.03   146.6 1033.47   150.8 1032.99
   157.5 1030.92   163.6  1030.6   170.1 1029.43     172 1029.31  179.21 1029.43
   193.2 1031.85   197.4 1034.53   210.9 1046.65   214.1 1049.08   220.3 1052.07
   226.6 1054.24   231.3 1055.25     244 1055.78   273.7 1054.63   286.3 1056.89
   299.1 1063.75   307.6 1067.74   324.5 1078.53   336.5 1083.73   346.9 1087.36
#Mann= 5 ,-1,0
       0     .05       0     100     .06       0   170.1    .045       0
  179.21     .06       0     200      .1       0
#XS Ineff= 2 , 0
           85.96 1036.86
Permanent Ineff=
       F       F
Bank Sta=170.1,179.21
XS Rating Curve= 0 ,0
Exp/Cntr(USF)=0,0
Exp/Cntr=0.3,0.1

Type RM Length L Ch R = 1 ,8427    ,495.5,497.7,499.8
XS GIS Cut Line= 2
1639015.97856889436547.0842417031639230.56248132436331.546622996
#Sta/Elev= 30
       0 1049.47     5.9 1046.96    17.2 1041.67    26.2 1038.19    31.8  1036.8
    44.3  1035.1    55.6 1032.48    72.6 1031.21   109.4 1031.05   126.3 1030.56
   151.8 1030.26     156 1029.96   165.9  1028.3   174.4  1028.5   177.3 1028.21
   178.6 1027.97     1841025.862   189.9 1025.11   199.9 1025.84   204.3 1027.05
   211.2 1030.82     227  1037.6   239.5 1044.67   245.1 1047.25   256.5 1050.89
   264.9 1054.08   272.3 1056.11   284.7 1060.14   293.2 1062.26   304.1 1064.02
#Mann= 5 ,-1,0
       0     .06       0      30     .05       0     170      .1       0
     184    .045       0   199.9      .1       0
Bank Sta=184,199.9
XS Rating Curve= 0 ,0
Exp/Cntr(USF)=0,0
Exp/Cntr=0.3,0.1

Type RM Length L Ch R = 1 ,7930    ,308.9,312.5,314.8
XS GIS Cut Line= 4
1639345.59265993436840.0563080661639389.03927923436819.922508875
1639528.91619993436753.1630694531639579.78053473436721.372860204
#Sta/Elev= 30
       0 1038.15    10.6  1033.5      16 1031.66    20.4 1030.53    29.2  1029.2
    51.3 1027.72    94.7  1026.5   108.9 1024.21   114.61022.452   117.8 1021.82
   122.2 1021.72   126.6 1022.46   131.1 1024.13   135.5 1024.82   144.4 1025.29
   148.8  1026.7   154.7 1029.76   179.8 1045.21   184.3 1047.14   188.7 1048.55
   197.6 1050.48     202 1052.19   220.8 1060.63   225.5 1061.77   230.2 1062.44
   234.7 1064.88   239.7 1068.98   246.3 1073.47   253.8 1077.19   262.9 1080.81
#Mann= 5 ,-1,0
       0      .1       0   67.89     .06       0   114.6    .045       0
   126.6     .06       0  177.89      .1       0
Bank Sta=114.6,126.6
XS Rating Curve= 0 ,0
Exp/Cntr(USF)=0,0
Exp/Cntr=0.3,0.1

Type RM Length L Ch R = 1 ,7617    ,203.6,207.6,209.7
XS GIS Cut Line= 4
1639433.13471812 437083.884945671639500.24738209437077.997869883
1639658.02101318437074.4656244111639762.81096218437067.401133466
#Sta/Elev= 30
       0 1061.23     9.5 1057.61    27.1 1051.76      48 1044.27    63.2 1039.12
    79.2 1034.78    82.1 1033.67    87.2 1031.12    91.2 1027.69    95.2 1023.38
    99.2 1021.21   103.2 1020.89   115.2 1021.92   119.3 1022.06   123.3 1021.26
   127.3 1019.91   129.31019.577   131.2 1019.26   139.3  1019.1   143.3 1019.38
   143.71019.574   147.3 1021.09   151.3 1023.65   155.3 1024.26   179.3 1023.98
   187.3 1024.11   219.3 1026.12   247.3 1026.82   319.5 1029.41   330.2 1029.97
#Mann= 6 ,-1,0
       0      .1       0   67.37     .06       0   129.3    .045       0
   143.7     .06       0  167.37      .1       0  265.18     .05       0
Bank Sta=129.3,143.7
XS Rating Curve= 0 ,0
Exp/Cntr(USF)=0,0
Exp/Cntr=0.3,0.1

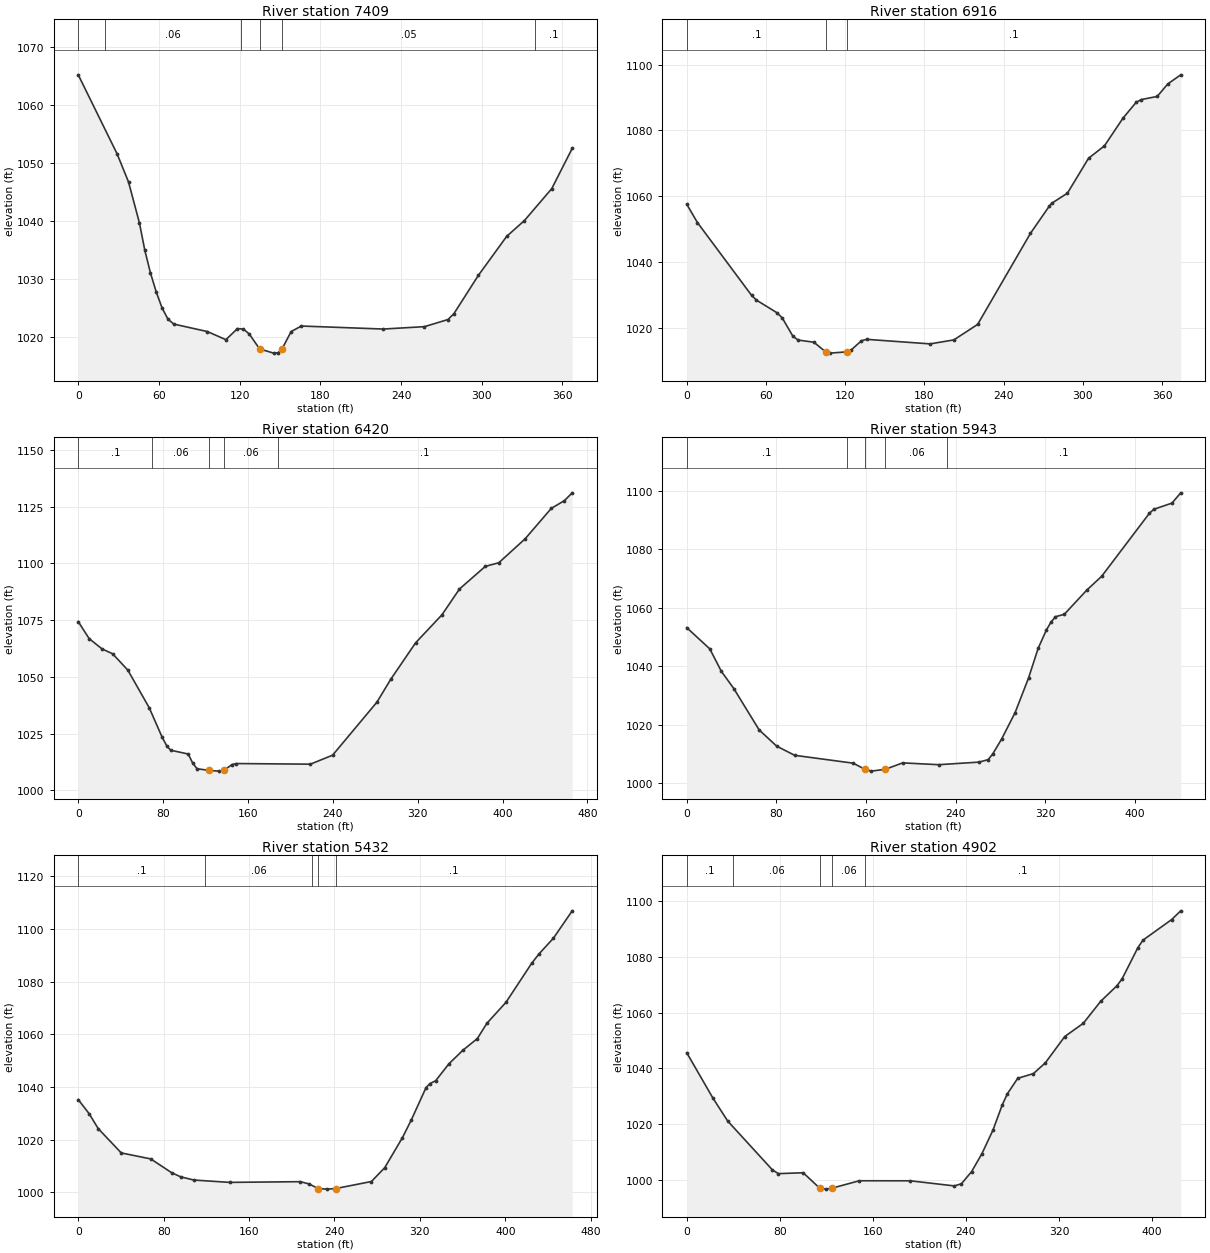
Type RM Length L Ch R = 1 ,7409    ,496.3,493.7,490.6
XS GIS Cut Line= 4
1639387.21552698437232.2392554971639437.84437875437240.481161599
 1639566.1826309437292.2874285231639728.66592262437364.109753122
#Sta/Elev= 30
       0 1065.22    28.9 1051.57    37.4 1046.71    45.5 1039.64    49.5 1034.92
    53.7    1031    58.1 1027.65    62.4 1024.93    66.7 1023.04      71 1022.18
    96.1 1020.88   109.8 1019.48   118.4  1021.4   122.8 1021.31   127.1 1020.48
   134.9 1017.88   145.3 1017.16   148.6 1017.22   151.4 1017.82   158.3 1020.88
   165.9 1021.84   226.8 1021.32   257.4 1021.73   274.9 1022.96   279.3 1023.96
   297.5 1030.58   318.6 1037.33   331.8 1040.06   352.1 1045.57   367.3 1052.52
#Mann= 6 ,-1,0
       0      .1       0      20     .06       0   121.3     .05       0
   134.9    .045       0   151.4     .05       0   339.7      .1       0
Bank Sta=134.9,151.4
XS Rating Curve= 0 ,0
Exp/Cntr(USF)=0,0
Exp/Cntr=0.3,0.1

Type RM Length L Ch R = 1 ,6916    ,492.6,495.8,496.8
XS GIS Cut Line= 4
1639324.07302421437745.8506811031639376.52686947437741.082149716
1639571.08295008 437742.989562271639697.92588498437742.035855993
#Sta/Elev= 30
       0 1057.56     8.1 1051.99    49.1 1029.87    52.8 1028.42    68.3 1024.59
    72.3 1023.03    80.3 1017.51    84.3 1016.29    96.3 1015.62   105.3 1012.66
   108.3 1012.31   121.5  1012.7   124.3 1013.19   132.3 1016.07   136.3  1016.5
   184.3 1015.12   202.3 1016.33   220.3 1021.04   260.3 1048.72   274.5 1056.95
   276.3 1057.83   288.3 1060.93   304.3 1071.54   316.3  1075.3   330.4 1083.74
   340.3 1088.52   344.3 1089.39   356.3 1090.33   364.3 1094.13   374.1  1096.9
#Mann= 3 ,-1,0
       0      .1       0   105.3    .045       0   121.5      .1       0
Bank Sta=105.3,121.5
XS Rating Curve= 0 ,0
Exp/Cntr(USF)=0,0
Exp/Cntr=0.3,0.1

Type RM Length L Ch R = 1 ,6420    ,478.1,477.3,475.3
XS GIS Cut Line= 4
1639225.86048847438192.1589909671639303.56988886438202.755727383
1639539.05292033438261.6264852511639679.16532406438296.948939972
#Sta/Elev= 30
       0 1074.34    10.3 1066.84    22.5 1062.29    32.4 1060.17    46.7    1053
    66.9 1036.39      79 1023.49    83.6 1019.44    87.2 1017.64   103.7 1015.97
   107.9 1011.97     112 1009.49   123.31008.748   132.6 1008.43   137.2 1008.72
     145 1011.33   149.1 1011.77   218.9  1011.5   239.8 1015.46   281.6 1038.84
   294.7 1048.97   318.1 1065.02   342.9 1077.34   359.4 1088.71   383.7 1098.67
   396.5  1100.3   421.3 1110.84     446 1124.27   458.4 1127.69   465.7 1131.12
#Mann= 5 ,-1,0
       0      .1       0      70     .06       0   123.3    .045       0
   137.2     .06       0  188.43      .1       0
Bank Sta=123.3,137.2
XS Rating Curve= 0 ,0
Exp/Cntr(USF)=0,0
Exp/Cntr=0.3,0.1

Type RM Length L Ch R = 1 ,5943    ,511.3,510.2,502.8
XS GIS Cut Line= 4
1639088.12127503438621.5133666881639144.63720258438667.432557825
1639370.70091279  438687.44861551639511.99073168 438692.15827613
#Sta/Elev= 30
       0 1053.21    20.6 1045.95    30.9 1038.28      42 1032.41    64.7 1018.24
    80.3 1012.73    96.4 1009.59   148.6 1006.91   159.1 1004.83   164.7 1004.19
   177.31004.815   192.8 1007.01   224.9 1006.39     261 1007.27   269.1 1008.11
   273.1 1009.98   281.1  1015.1   293.2 1024.17   305.2 1035.99   313.8 1046.14
   321.2 1052.44   325.2 1055.07   329.2 1056.93   337.2 1057.79   357.2 1066.03
   370.5 1070.75   413.2 1092.32   417.2 1093.67   433.3 1095.76   441.1 1099.27
#Mann= 5 ,-1,0
       0      .1       0  142.82     .06       0   159.1    .045       0
   177.3     .06       0  232.82      .1       0
Bank Sta=159.1,177.3
XS Rating Curve= 0 ,0
Exp/Cntr(USF)=0,0
Exp/Cntr=0.3,0.1

Type RM Length L Ch R = 1 ,5432    ,528.6,530.7,527.5
XS GIS Cut Line= 4
1639198.68840853439167.5753867041639271.80588981439137.904524738
 1639500.6953964439073.2644325991639632.09492796439009.684014101
#Sta/Elev= 30
       0 1035.24    10.2 1029.88    18.8 1024.18    40.3 1014.99    67.9 1012.72
    87.5 1007.48    95.9 1005.93   108.3  1004.7   141.8 1003.81   208.1 1004.08
   216.4 1003.19   224.7 1001.48     233 1001.25   241.3 1001.48   274.6 1004.14
   287.1 1009.39   303.7 1020.81     312 1027.51   325.8  1039.8   329.4 1041.29
   334.8 1042.39   347.2 1048.81   360.5 1054.03   373.9 1058.41   382.7 1064.15
   400.7 1072.16   424.7 1086.94   431.6 1090.52     445 1096.43   462.7 1106.87
#Mann= 5 ,-1,0
       0      .1       0  118.91     .06       0  218.91      .1       0
   224.7    .045       0   241.3      .1       0
Bank Sta=224.7,241.3
XS Rating Curve= 0 ,0
Exp/Cntr(USF)=0,0
Exp/Cntr=0.3,0.1

Type RM Length L Ch R = 1 ,4902    ,527,533.9,530.6
XS GIS Cut Line= 4
 1639366.8387867439576.4063653351639426.92228218 439555.42482723
1639623.38577533439466.7301434261639753.08982907439400.924410281
#Sta/Elev= 30
       0 1045.61    22.5 1029.38    35.2 1021.18    73.7 1003.67    78.8 1002.36
   100.1 1002.68   114.3997.1595   119.3  996.82   124.7997.1469   148.3  999.81
   192.2   999.8     230  997.97   236.1  998.74   244.9 1003.11   253.7 1009.49
   263.3 1018.02   271.2 1026.96   275.6 1030.92   284.5 1036.46     298 1038.16
   308.2 1041.98   324.9  1051.4   340.9 1056.16   355.8 1064.01   369.7 1069.55
   374.2 1072.03   387.7 1083.15   392.1 1085.88   416.7 1093.22   424.6 1096.38
#Mann= 5 ,-1,0
       0      .1       0      40     .06       0   114.3    .045       0
   124.7     .06       0  153.64      .1       0
Bank Sta=114.3,124.7
XS Rating Curve= 0 ,0
Exp/Cntr(USF)=0,0
Exp/Cntr=0.3,0.1