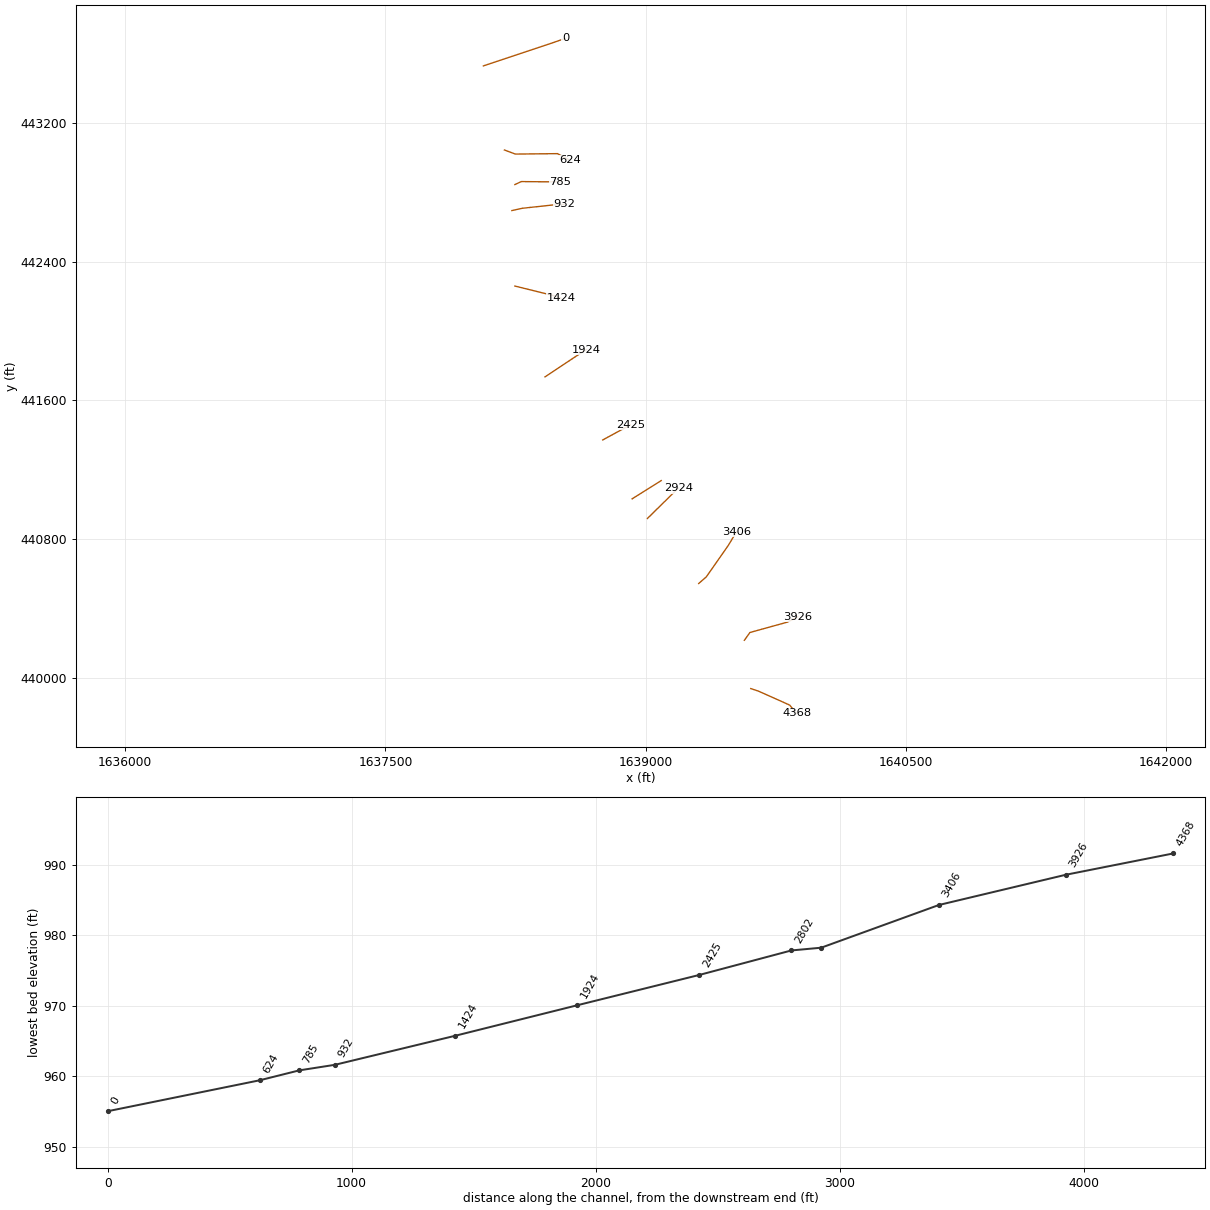
HEC-RAS study MFKLYNCPRN.prj: MFKLYNCPRN

--- MFKLYNCPRN.g01 (geometry) --- (continued)

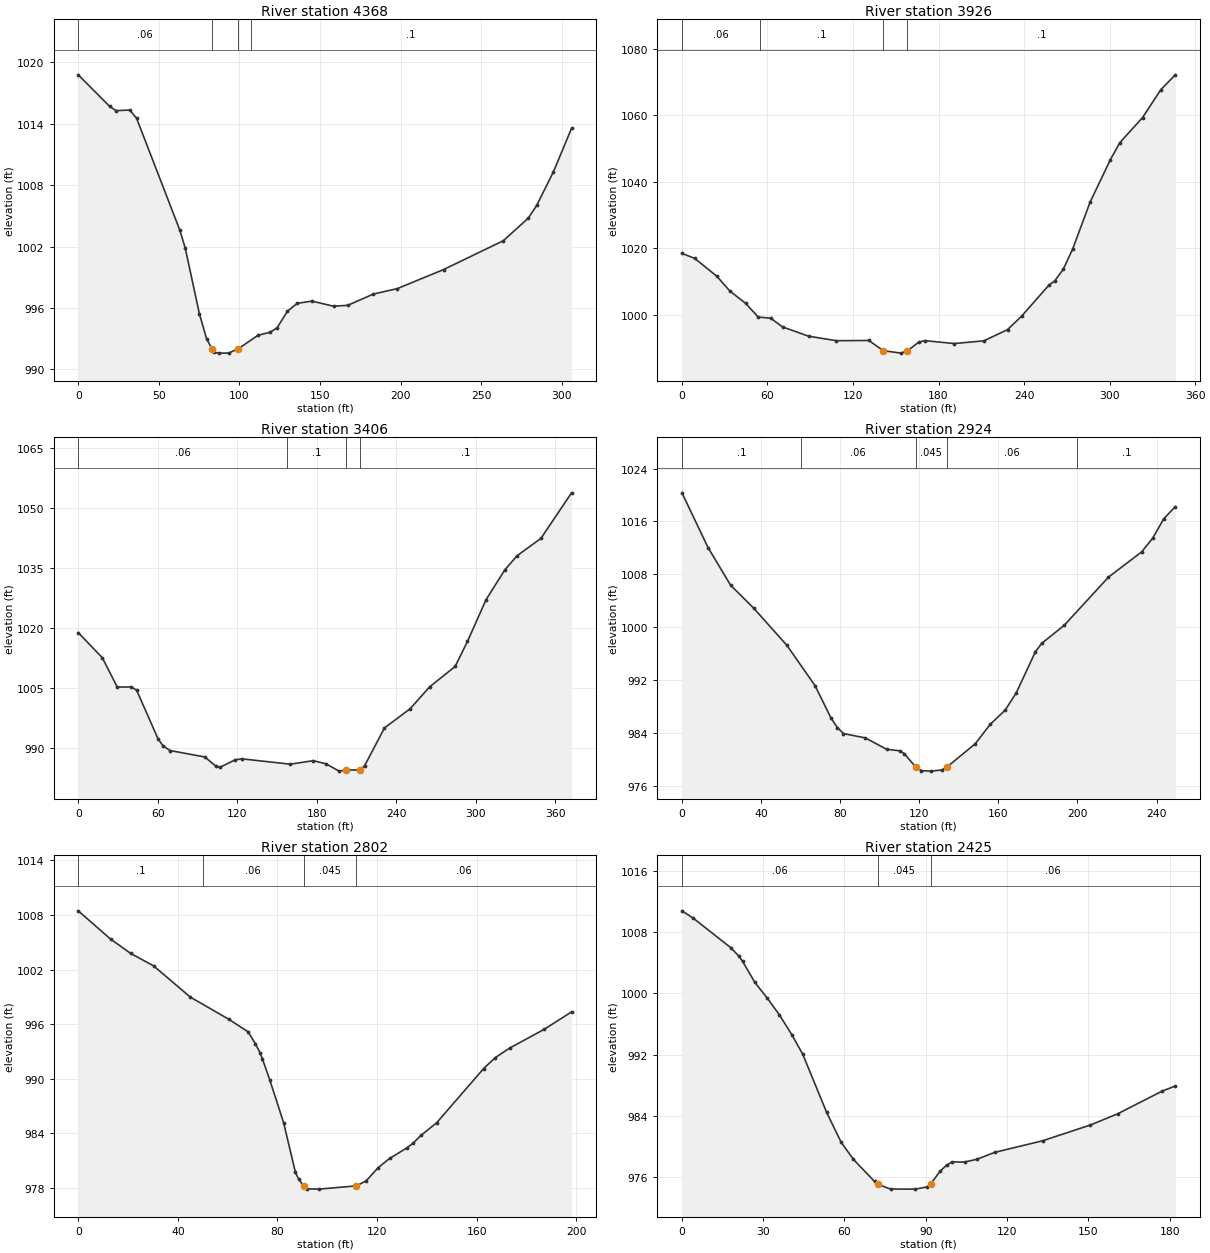
Type RM Length L Ch R = 1 ,4368    ,435.9,441.7,444.8
XS GIS Cut Line= 4
1639605.79643353439938.9403686851639650.30272647439924.104937702
1639830.44724555439843.5697409381639869.65517029439795.884427065
#Sta/Elev= 30
       0 1018.77    19.5 1015.69    23.5 1015.27      32 1015.33    36.2 1014.53
    63.1 1003.57    66.4 1001.84    75.2  995.41    79.6  993.01    83.1  991.97
    84.3  991.66    87.3  991.59    93.4   991.6    99.4  992.03   111.5  993.33
     119  993.63   123.4  994.07   129.7  995.67   135.8  996.45   144.9  996.67
   158.4  996.17   167.2  996.26   183.1  997.36   197.9  997.89   226.6  999.75
   263.7 1002.57   279.2 1004.78   284.4 1006.02   294.8 1009.31     306 1013.55
#Mann= 4 ,-1,0
       0     .06       0    83.1    .045       0    99.4     .06       0
  106.91      .1       0
Bank Sta=83.1,99.4
XS Rating Curve= 0 ,0
Exp/Cntr(USF)=0,0
Exp/Cntr=0.3,0.1

Type RM Length L Ch R = 1 ,3926    ,514,519.7,523.3
XS GIS Cut Line= 4
1639569.13895484440217.2042671531639600.92916409440261.946043133
1639817.57355304440321.9942161581639876.44431091 440352.60701025
#Sta/Elev= 30
       0  1018.5       9 1016.99    24.6  1011.6    33.5 1007.24    44.7  1003.5
    53.5  999.39    62.3  999.04    70.6  996.42    88.8  993.65   108.3  992.29
   131.1  992.36   141.2   989.3   153.7  988.56   158.2989.2708   166.1  991.84
   170.3  992.31     191  991.44   211.8  992.25   228.4  995.61   238.3  999.66
   257.4 1008.95   261.6 1010.27   267.6 1013.81   274.1 1019.81   286.4 1033.95
   300.6 1046.66   307.2 1051.74   323.1 1059.25     336 1067.67   346.1  1072.1
#Mann= 4 ,-1,0
       0     .06       0   54.89      .1       0   141.2    .045       0
   158.2      .1       0
Bank Sta=141.2,158.2
XS Rating Curve= 0 ,0
Exp/Cntr(USF)=0,0
Exp/Cntr=0.3,0.1

Type RM Length L Ch R = 1 ,3406    ,482.7,482.2,480.9
XS GIS Cut Line= 4
1639305.82265375440544.6215306971639349.38701457440582.298815733
1639475.37043641 440762.443334811639524.82187302440843.684980668
#Sta/Elev= 30
       0 1018.84    18.2 1012.56    29.5 1005.25      40 1005.28    44.1 1004.48
    60.3  992.31      64  990.61    69.3  989.42    95.6  987.81   104.2  985.44
   107.1  985.24   118.6  987.12   123.8  987.34   160.1  986.01   177.5  986.89
   187.2  986.09     197  984.28   201.9  984.56   212.6984.5634   216.3  985.65
   231.2  995.04   250.7  999.86   265.3 1005.29   284.6 1010.39   293.9 1016.63
     308 1027.08     322 1034.43   331.4 1038.02   349.4 1042.34   372.5  1053.7
#Mann= 4 ,-1,0
       0     .06       0   157.6      .1       0   201.9    .045       0
   212.6      .1       0
Bank Sta=201.9,212.6
XS Rating Curve= 0 ,0
Exp/Cntr(USF)=0,0
Exp/Cntr=0.3,0.1

Type RM Length L Ch R = 1 ,2924    ,124.9,122.2,120
XS GIS Cut Line= 2
1639010.23773854440919.2670038611639188.26291033441094.113154729
#Sta/Elev= 30
       0 1020.33    13.2 1012.05    24.6 1006.36    36.2 1002.91    53.1  997.25
    67.3  991.17    75.5   986.2    78.6  984.82    81.7  983.91    92.7  983.26
   103.5  981.54   110.3   981.3   112.5  980.86   118.2  978.85     121  978.31
     126  978.23   131.6  978.42   133.8978.7933   148.4  982.39   155.9  985.31
   163.5  987.46   169.1  990.09   178.8  996.31     182  997.57   193.3 1000.28
   215.7 1007.57   232.5  1011.4   238.1 1013.48   243.7 1016.42   249.5 1018.24
#Mann= 5 ,-1,0
       0      .1       0      60     .06       0   118.2    .045       0
   133.8     .06       0     200      .1       0
Bank Sta=118.2,133.8
XS Rating Curve= 0 ,0
Exp/Cntr(USF)=0,0
Exp/Cntr=0.3,0.1

Type RM Length L Ch R = 1 ,2802    ,376.9,377.3,375.6
XS GIS Cut Line= 2
1638922.22560531441032.4392977631639089.97195529441137.742623191
#Sta/Elev= 30
       0 1008.46      13 1005.35    21.1 1003.77    30.3  1002.4      45  998.97
    60.4  996.54    68.2  995.15    71.1  993.86    73.1   992.8      74  992.14
    76.9  989.88    82.5  985.13    87.2  979.71    88.5  978.94    90.5  978.21
      92  977.87    96.7  977.84   111.7   978.2   115.6  978.74   120.4  980.19
     125  981.21     132  982.38   134.5  982.91   137.8  983.79   143.9  985.13
   162.8  991.11   167.5  992.31   173.2  993.35   187.1  995.42   198.1  997.34
#Mann= 4 ,-1,0
       0      .1       0      50     .06       0    90.5    .045       0
   111.7     .06       0
Bank Sta=90.5,111.7
XS Rating Curve= 0 ,0
Exp/Cntr(USF)=0,0
Exp/Cntr=0.3,0.1

Type RM Length L Ch R = 1 ,2425    ,499.9,500.9,502
XS GIS Cut Line= 2
1638752.46272417441371.7381515911638912.47344406441458.631390204
#Sta/Elev= 30
       0 1010.82     4.2 1009.85      18    1006      21 1004.89    22.4 1004.19
    26.9 1001.45    31.5  999.38      36  997.18    40.6  994.57    44.6  992.03
    53.4  984.43    58.8  980.48    63.3  978.27    71.1  975.37    72.4  974.98
      77  974.38    86.1  974.37    90.6  974.67    91.8  975.02    95.2  976.69
    97.7  977.51    99.7  977.93   104.3  977.92   108.8  978.27   115.4  979.18
   133.1   980.7   150.8  982.77   160.9  984.25   177.1  987.18   182.1  987.88
#Mann= 3 ,-1,0
       0     .06       0    72.4    .045       0    91.8     .06       0
Bank Sta=72.4,91.8
XS Rating Curve= 0 ,0
Exp/Cntr(USF)=0,0
Exp/Cntr=0.3,0.1

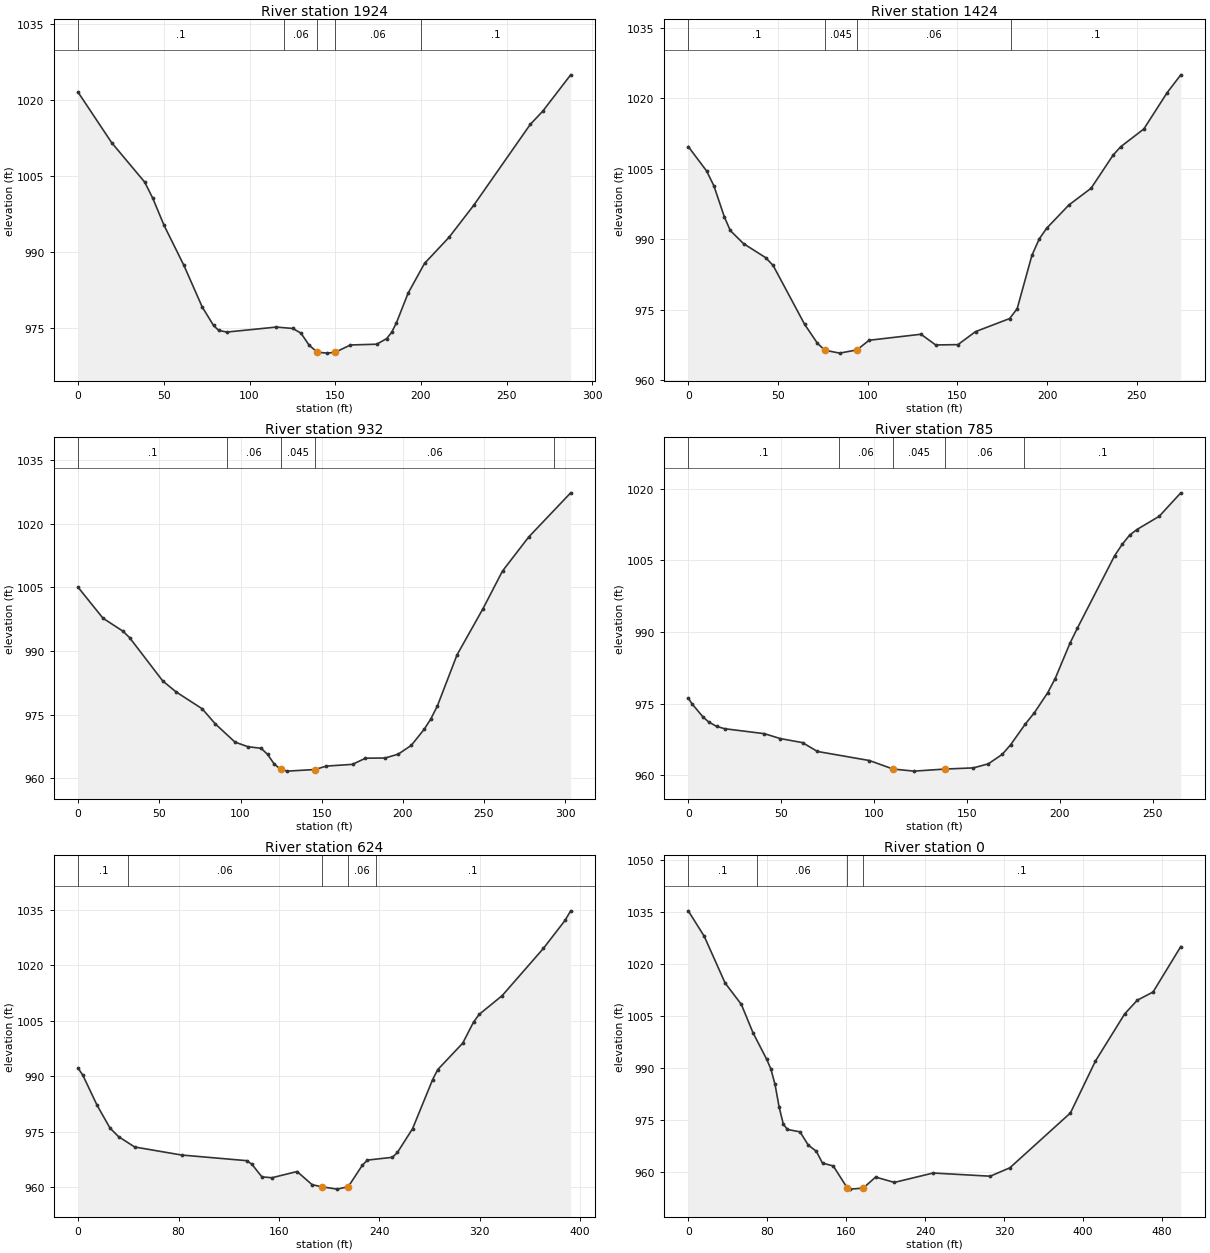
Type RM Length L Ch R = 1 ,1924    ,506.6,499.8,492
XS GIS Cut Line= 3
1638419.81771753441735.3301276611638619.97829428441868.378040443
1638660.01040963441893.103758748
#Sta/Elev= 30
       0 1021.53    19.6 1011.58    38.8 1003.83    43.6 1000.59    50.1   995.3
    61.7  987.39    72.4  979.17      79  975.53      82  974.55    86.8  974.23
   115.6  975.21   125.2  974.94     130  974.02   134.8  971.62   139.6  970.26
   139.6  970.25   145.3  970.07     150970.2428   158.9  971.68   174.2  971.83
     180  972.93   182.9  974.16   185.7  976.04   192.5  981.88   202.1  987.77
   216.5  992.96   230.9  999.28   263.8  1015.2   271.1 1017.82   287.4 1024.99
#Mann= 5 ,-1,0
       0      .1       0     120     .06       0   139.6    .045       0
     150     .06       0     200      .1       0
Bank Sta=139.6,150
XS Rating Curve= 0 ,0
Exp/Cntr(USF)=0,0
Exp/Cntr=0.3,0.1

Type RM Length L Ch R = 1 ,1424    ,488.8,492.4,495.5
XS GIS Cut Line= 3
1638246.22178793442258.9968082371638479.34998908442201.303465526
1638511.14019833442188.351898795
#Sta/Elev= 30
       0 1009.73    10.2 1004.54    14.3 1001.35    20.1  994.77    23.4  991.86
    30.8  989.06    43.2  986.06    47.3  984.41    64.9  971.85      72  967.84
    76.1  966.37    84.4  965.75      94966.4409   100.8  968.49   129.7  969.77
   137.9  967.49   150.3  967.56   160.1  970.33   179.1  973.11   183.3   975.2
   191.5  986.54   195.6  990.06   199.7  992.32   212.1  997.28   224.5 1000.85
   236.8 1007.92     241 1009.69   253.9 1013.47   266.9 1021.21   274.5    1025
#Mann= 4 ,-1,0
       0      .1       0    76.1    .045       0      94     .06       0
     180      .1       0
Bank Sta=76.1,94
XS Rating Curve= 0 ,0
Exp/Cntr(USF)=0,0
Exp/Cntr=0.3,0.1

Type RM Length L Ch R = 1 ,932     ,146.7,146.3,144.6
XS GIS Cut Line= 4
1638229.16325103442694.0884508781638289.34224797442707.170841515
1638469.87923876442726.7944274711638530.05823569442729.410905599
#Sta/Elev= 30
       0    1005    15.3  997.72    27.6  994.66    31.7  993.13    52.1  982.92
    60.3  980.34    76.4  976.35    84.5  972.78    96.6  968.49   104.6   967.4
   112.7  967.03   116.7  965.58   120.7  963.36   124.7  962.05   128.7  961.64
   145.9  962.02   152.9  962.83     169  963.24     177  964.69   189.1  964.74
   197.2  965.65   205.2  967.72   213.2  971.54   217.3     974   221.3  977.04
   233.4  989.09   249.4  999.99   261.4 1008.86   277.5 1016.87   303.4 1027.31
#Mann= 5 ,-1,0
       0      .1       0   91.58     .06       0   124.7    .045       0
   145.9     .06       0  293.18      .1       0
Bank Sta=124.7,145.9
XS Rating Curve= 0 ,0
Exp/Cntr(USF)=0,0
Exp/Cntr=0.3,0.1

Type RM Length L Ch R = 1 ,785     ,162.7,161.6,162.3
XS GIS Cut Line= 3
 1638246.3498315442843.8879511751638283.54437632 442861.05466417
1638507.66535152442859.147251615
#Sta/Elev= 30
       0  976.15     1.9     975     7.8  972.25    10.9  971.17    15.2  970.23
    19.6  969.73      41  968.69    49.5  967.67    61.5  966.82    69.5  964.97
    97.5  963.07   110.2961.2888   121.5  960.85   138.2961.2833   153.5  961.53
   161.5  962.38     169  964.36   173.5  966.37   181.5  970.76   186.3  973.08
   193.5   977.3   197.5  980.24   205.5  987.68   209.5  990.84   229.5 1005.97
   233.5 1008.31   237.5 1010.24   241.5 1011.45   253.5 1014.22   265.1 1019.13
#Mann= 5 ,-1,0
       0      .1       0   80.96     .06       0   110.2    .045       0
   138.2     .06       0  180.96      .1       0
Bank Sta=110.2,138.2
XS Rating Curve= 0 ,0
Exp/Cntr(USF)=0,0
Exp/Cntr=0.3,0.1

Type RM Length L Ch R = 1 ,624     ,619.7,623.8,625.2
XS GIS Cut Line= 4
1638185.98184696443043.1437935791638248.77732202443019.595490431
1638492.10978788443022.2119685591638564.06293638442982.964796647
#Sta/Elev= 30
       0  992.12     3.7  990.26    15.1   982.1    25.4  975.94    32.2  973.64
      45  970.84    82.4  968.67   134.4  967.14   138.4  966.18   146.4  962.76
   154.4  962.53   174.4  964.21   186.4  960.65   194.4960.0643   206.4  959.45
   215.2  960.11   226.4  965.91   230.4   967.3   250.4  968.05   254.4  969.38
   266.4  975.77   282.4  989.05   286.4  991.73   306.4  998.92     315  1004.6
   319.5 1006.69   337.8 1011.75   370.6  1024.5   387.9 1032.09   392.4 1034.68
#Mann= 5 ,-1,0
       0      .1       0      40     .06       0   194.4    .045       0
   215.2     .06       0  237.07      .1       0
Bank Sta=194.4,215.2
XS Rating Curve= 0 ,0
Exp/Cntr(USF)=0,0
Exp/Cntr=0.3,0.1

Type RM Length L Ch R = 1 ,0       ,405.4,411.9,408.4
XS GIS Cut Line= 3
 1638064.7435333443527.8182915621638455.68867899443658.133340126
1638537.80501096443686.695542551
#Sta/Elev= 30
       0 1035.38    16.2 1028.02    37.3 1014.56    53.8 1008.36    65.5 1000.24
    79.4  992.56    83.7  989.73    87.9  985.28    92.1  978.68    96.3  973.81
   100.5  972.28   113.2  971.59   121.6  967.76   129.7     966     136  962.57
   146.9  961.75   161.3   955.3   163.8  955.06   177.2  955.35   189.8  958.54
   208.8     957   248.1  959.71   305.9  958.79   325.8  961.21   387.2  977.05
   412.5  992.01   442.2 1005.65   454.9 1009.58   470.9 1011.95     499 1025.07
#Mann= 4 ,-1,0
       0      .1       0      70     .06       0   161.3    .045       0
   177.2      .1       0
Bank Sta=161.3,177.2
XS Rating Curve= 0 ,0
Exp/Cntr=0.3,0.1
LCMann Table=0

Chan Stop Cuts=-1
Use User Specified Reach Order=0
Composite Channel Slope=5